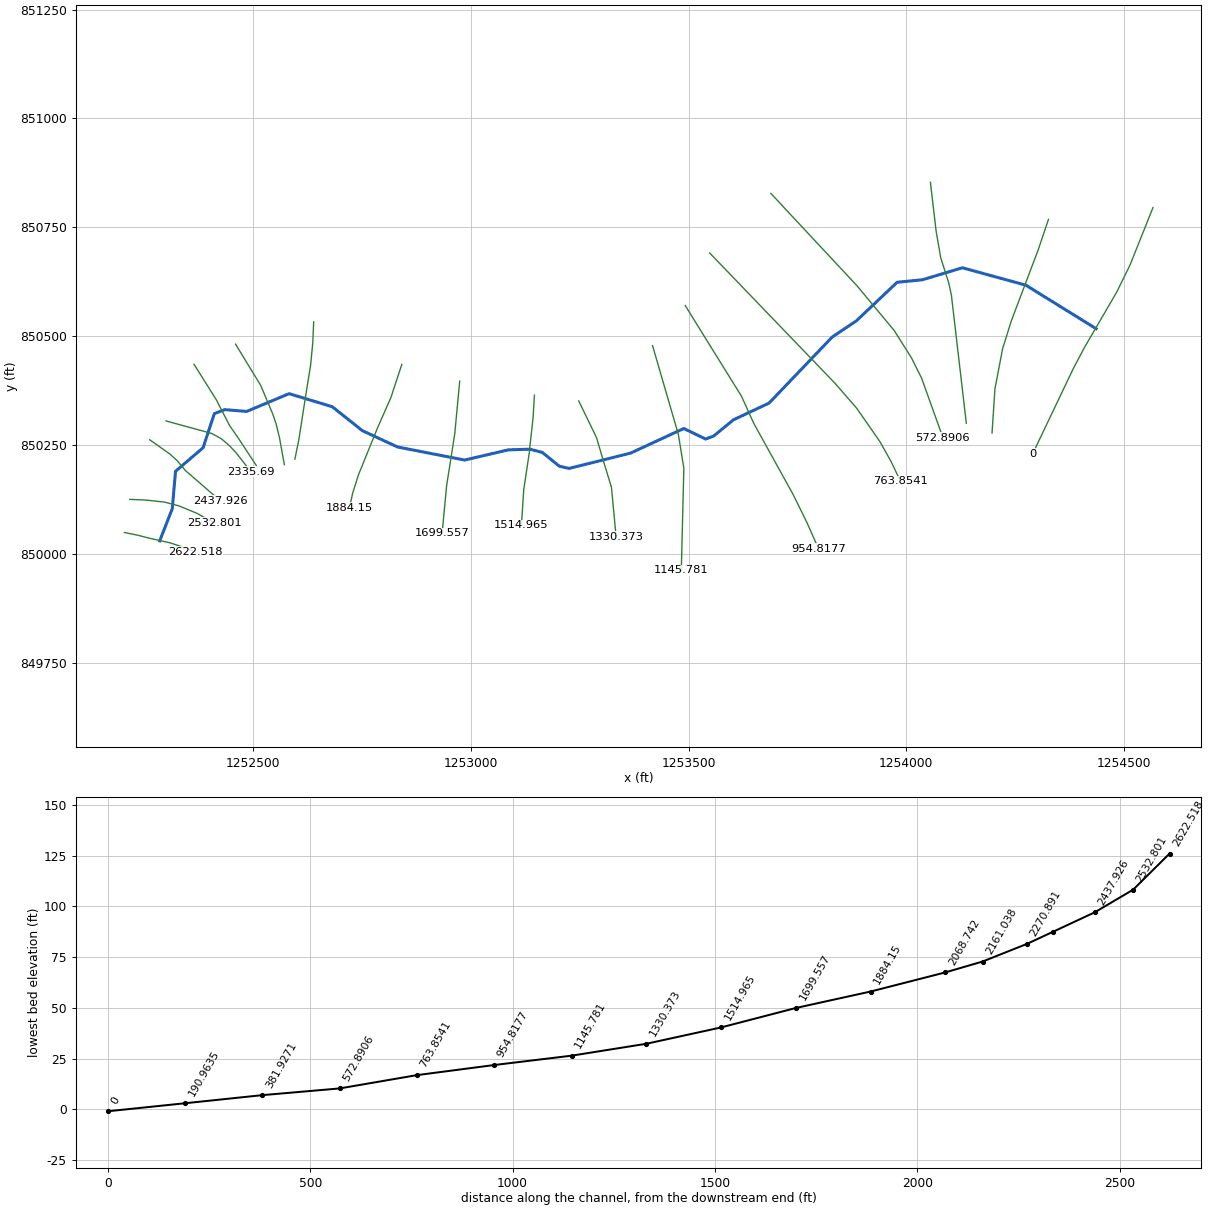
--- 190_ras.prj (project) ---

Proj Title=190
Current Plan=p01
Default Exp/Contr=0.3,0.1
English Units
Geom File=g01
Flow File=f01
Plan File=p01
Y Axis Title=Elevation
X Axis Title(PF)=Main Channel Distance
X Axis Title(XS)=Station
BEGIN DESCRIPTION:
RFD model 190 exported to HEC-RAS
END DESCRIPTION:

--- 190_ras.p01 (plan) ---

Plan Title=Plan 01
Program Version=4.10
Short Identifier=Plan 01
Geom File=g01
Flow File=f01
Subcritical Flow
Calc Critical at every XS
Secant Critical Depth

--- 190_ras.f01 (steady flow) ---

Flow Title=Flow 01
Program Version=5.01
Number of Profiles= 5
Profile Names=10yr,25yr,50yr,100yr,500yr
River Rch & RM=190,18,2622.518
  194.07  348.59  500.59  685.57 1249.42
River Rch & RM=190,18,2532.801
  206.34  371.13  533.64  731.84 1338.74
River Rch & RM=190,18,2437.926
  210.63  379.02  545.21  748.06 1370.12
River Rch & RM=190,18, 2335.69
   214.3  385.77  555.14  761.98 1397.07
River Rch & RM=190,18,2161.038
  246.07  444.31  641.23   882.9 1632.43
River Rch & RM=190,18,2068.742
  256.43  463.43   669.4  922.56 1710.04
River Rch & RM=190,18, 1884.15
   268.6  485.92  702.57  969.29 1801.72
River Rch & RM=190,18,1699.557
   293.5     532  770.63 1065.33 1990.92
River Rch & RM=190,18,1514.965
  301.99  547.73  793.89 1098.19 2055.89
River Rch & RM=190,18,1330.373
  308.04  558.96  810.51 1121.68 2102.41
River Rch & RM=190,18,1145.781
  323.78  588.15  853.74 1182.84 2223.76
River Rch & RM=190,18,954.8177
  360.01  655.49   953.6 1324.37 2505.94
River Rch & RM=190,18,763.8541
  393.73  718.29 1046.92 1456.93  2771.8
River Rch & RM=190,18,572.8906
  400.34  730.62 1065.27 1483.02 2824.29
River Rch & RM=190,18,381.9271
  456.12  834.81 1220.52 1704.18 3271.29
River Rch & RM=190,18,190.9635
  462.11     846 1237.23 1728.02 3319.68
River Rch & RM=190,18,       0
  554.61 1019.42 1496.57  2098.9 4077.12
Boundary for River Rch & Prof#=190,18,1
Up Type= 0
Dn Type= 2
Boundary for River Rch & Prof#=190,18,2
Up Type= 0
Dn Type= 2
Boundary for River Rch & Prof#=190,18,2
Up Type= 0
Dn Type= 2
Boundary for River Rch & Prof#=190,18,2
Up Type= 0
Dn Type= 2
Boundary for River Rch & Prof#=190,18,2
Up Type= 0
Dn Type= 2

--- 190_ras.g01 (geometry) ---

Geom Title=190
Program Version=4.10

River Reach=190,18
Reach XY= 30
1252285.26035471850029.6257933811252314.10630129850103.682483589
1252321.60630162850189.5157913461252384.93961795850243.682440155
1252410.77294599850322.0157495941252434.93960583850331.182412824
1252484.93959103850327.015745927 1252582.4395636850367.849064349
1252681.60620027850337.8490702951252750.77284502 850282.84908455
1252831.60615351850245.3490932091252985.77277402850215.349097557
1253085.77274535850238.6824210831253135.77273072850240.349085772
1253164.10605552850232.8490871651253203.27270975850201.182428692
  1253225.772703850196.1824295251253366.60599601850231.182415052
 1253489.1059617850287.8490613491253539.10594632850263.682400396
1253557.43927446850270.3490645481253603.27259544850307.849052144
1253684.93923925850346.1823717411253829.93920112850497.848989341
1253885.77251917850535.3489766211253979.10582769850623.682281123
1254037.43914407850629.5156110261254129.10578462850657.015600214
1254274.93907396850617.0156077511254436.30510904850517.076999737

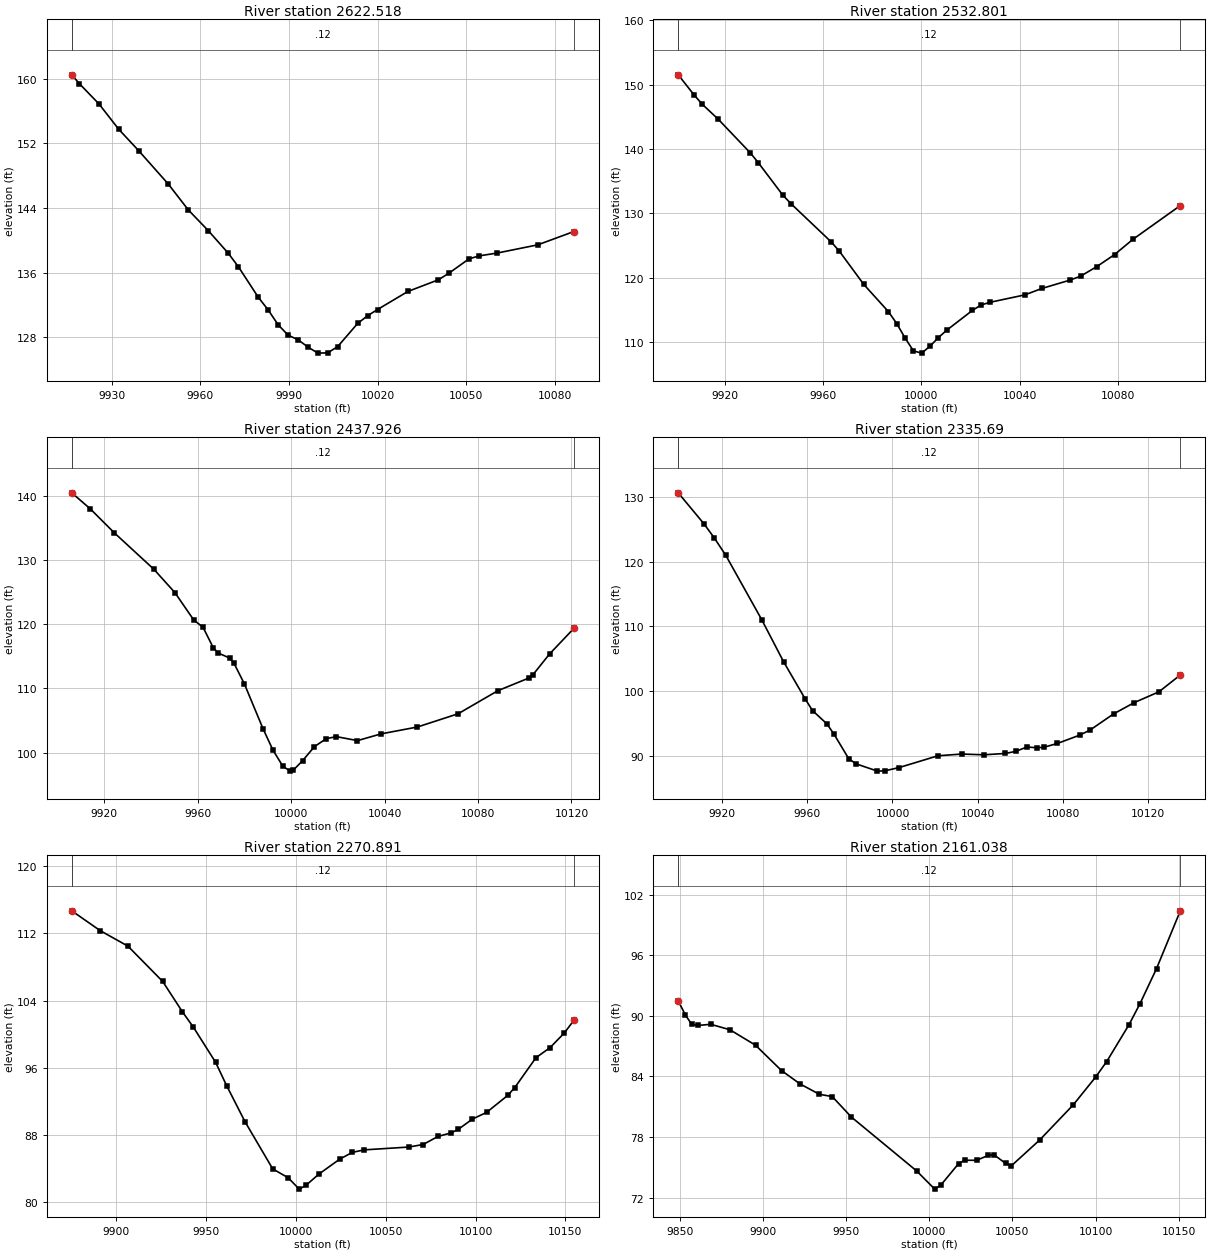
Type RM Length L Ch R = 1 ,2622.518,89.717200,89.717200,89.717200
XS GIS Cut Line= 6
1252203.96714607850048.9765946441252234.69631274850042.726594644
1252264.14441609850035.2233425521252308.70624942850025.270890943
1252343.31731435850013.8473726981252367.50881274850004.184927977
#Sta/Elev= 30
 9916.46160.45859918.987159.38359925.683156.84919932.379153.71169939.075151.0855
9949.134146.94179955.905 143.7439962.676141.17449969.448138.37479972.833136.7205
9979.593132.93549982.951131.36189986.309129.53319989.667128.25319993.025127.6849
9996.383126.78419999.737126.029510003.09126.066710006.46126.8415 10013.2129.7014
10016.56130.651910019.93131.425110030.19 133.65410040.56135.107710044.01135.8971
10050.92137.697710054.38 138.06310060.32138.403910074.16139.425810086.37141.0723
#Mann= 3 , 0 , 0
 9916.46    0.12       0 9916.46    0.12       010086.37    0.12       0
#XS Ineff= 2 , 0
       0                               0
Bank Sta=9916.46,10086.37
Exp/Cntr=0.3,0.1

Type RM Length L Ch R = 1 ,2532.801,94.874900,94.874900,94.874900
XS GIS Cut Line= 6
1252216.46714607850125.0182613111252251.78748447850123.559276538
1252295.84976009850118.8612680611252328.89795506850110.275690018
1252371.18357327850092.8231286311252410.19164333850070.671482798
#Sta/Elev= 30
9901.006151.53059907.393148.43789910.676146.99559917.243144.64959930.378139.3876
9933.662137.84449943.543132.85289946.841131.52559963.332125.54629966.635 124.103
9976.542118.95999986.603114.71149989.992112.85589993.382110.61379996.772108.6217
10000.16108.277110003.55109.375910006.94110.693710010.33111.842910020.77114.9173
10024.32115.758810027.87116.170210042.06117.323610049.16118.340810060.56119.6324
 10064.8120.232510071.44121.730810078.63123.588510086.17125.974310105.42 131.211
#Mann= 3 , 0 , 0
9901.006    0.12       09901.006    0.12       010105.42    0.12       0
#XS Ineff= 2 , 0
       0                               0
Bank Sta=9901.006,10105.42
Exp/Cntr=0.3,0.1

Type RM Length L Ch R = 1 ,2437.926,102.235800,102.235800,102.235800
XS GIS Cut Line= 6
1252262.30047941850261.9974279781252308.92379805850228.965494732
  1252325.818603850213.5336363481252344.29328086 850191.18514692
1252356.63979059850180.6509410421252424.27964607850121.893261311
#Sta/Elev= 30
9906.166140.54279914.106138.03449924.333134.30969941.359128.58679950.293124.9691
9958.335120.70469962.356119.5393  9966.7116.36829968.816115.53899973.681114.7516
9975.587113.9332 9980.03 110.7139988.016 103.7089992.278 100.3619996.53997.83103
9999.685  97.096   1000197.26501 10004.998.71001   10010100.9218 10015.1102.1722
10019.43102.479510028.42101.859410038.45 102.906 10054.1103.987710071.49106.0512
10088.48109.650410101.91111.652310103.49 112.135 10110.6115.378810121.01 119.373
#Mann= 3 , 0 , 0
9906.166    0.12       09906.166    0.12       010121.01    0.12       0
#XS Ineff= 2 , 0
       0                10017.61       0
Bank Sta=9906.166,10121.01
Exp/Cntr=0.3,0.1

Type RM Length L Ch R = 1 , 2335.69,64.799200,64.799200,64.799200
XS GIS Cut Line= 6
1252299.80047941850305.2265946441252404.56278115 850276.45903284
1252426.94356309850264.1726302141252443.96380603850249.843939363
1252459.98627144850233.0031762841252494.80292821850188.531583432
#Sta/Elev= 30
9899.217130.7125 9911.29125.92219916.059123.77969921.507 121.0689938.536111.0285
9948.753104.5514 9958.9798.755799962.37696.972889969.18394.899049972.58393.26423
9979.38489.531889982.78588.726779992.93987.588569996.346 87.631710003.1388.14374
10021.4189.9701610032.6490.2367410042.9190.11916 10053.190.3256110057.9190.64617
 10063.391.3318910068.06 91.2018 10071.591.3126510077.5891.8774110088.0793.16637
10092.9393.9513810104.0396.4625510113.7698.2127610125.32 99.875610135.39102.4863
#Mann= 3 , 0 , 0
9899.217    0.12       09899.217    0.12       010135.39    0.12       0
#XS Ineff= 2 , 0
       0                10031.48       0
Bank Sta=9899.217,10135.39
Exp/Cntr=0.3,0.1

Type RM Length L Ch R = 1 ,2270.891,109.853200,109.853200,109.853200
XS GIS Cut Line= 5
1252364.03659052850435.4349279781252415.25186829850353.837705755
1252445.63381274850294.8099279771252463.87005991  850268.5974592
1252510.41490175 850197.80092378
#Sta/Elev= 30
9875.316114.68219891.062112.33499906.557110.48249925.924106.27559936.818102.6872
 9942.99100.83629955.33396.664449961.504 93.87539971.65589.613559987.13183.97434
9995.708 82.924210001.8981.5666710005.5882.0100210012.9683.3760310024.3885.12713
10031.4185.9392410038.0486.2374810062.8386.5737510070.8186.8742110079.15 87.8424
10086.5288.2613910090.4488.69176 10098.389.9062610106.1590.6970410117.9392.72465
10121.8593.6560610133.6397.2094910141.4998.4072610149.34 100.136 10154.7101.6449
#Mann= 3 , 0 , 0
9875.316    0.12       09875.316    0.12       0 10154.7    0.12       0
#XS Ineff= 2 , 0
       0                10037.22       0
Bank Sta=9875.316,10154.7
Exp/Cntr=0.3,0.1

Type RM Length L Ch R = 1 ,2161.038,92.296000,92.296000,92.296000
XS GIS Cut Line= 6
1252459.52270163850481.4418724221252517.13255195850387.038632032
1252544.97133966850320.939303877 1252552.5694017850298.717968791
1252560.34805383850266.7276280481252571.65966591850204.623383005
#Sta/Elev= 30
9849.11491.495619853.29690.128769857.13989.182719860.83889.05517 9868.6789.16884
  9880.288.631129895.57487.099949911.22384.585059922.47983.249949934.00982.23554
9941.696 82.01139953.22779.980159992.63274.61739 10003.372.8405510006.8973.21866
10017.6775.3667210021.2675.7035510028.4575.6949410035.4976.1814210038.9676.24752
10045.8975.3941810049.3675.1443810066.3977.7024310086.6481.19519   1010083.93063
10106.6785.4670110120.0189.0963510126.6891.1942710136.68  94.68910150.98100.4136
#Mann= 3 , 0 , 0
9849.114    0.12       09849.114    0.12       010150.98    0.12       0
#XS Ineff= 2 , 0
       0                10037.24       0
Bank Sta=9849.114,10150.98
Exp/Cntr=0.3,0.1

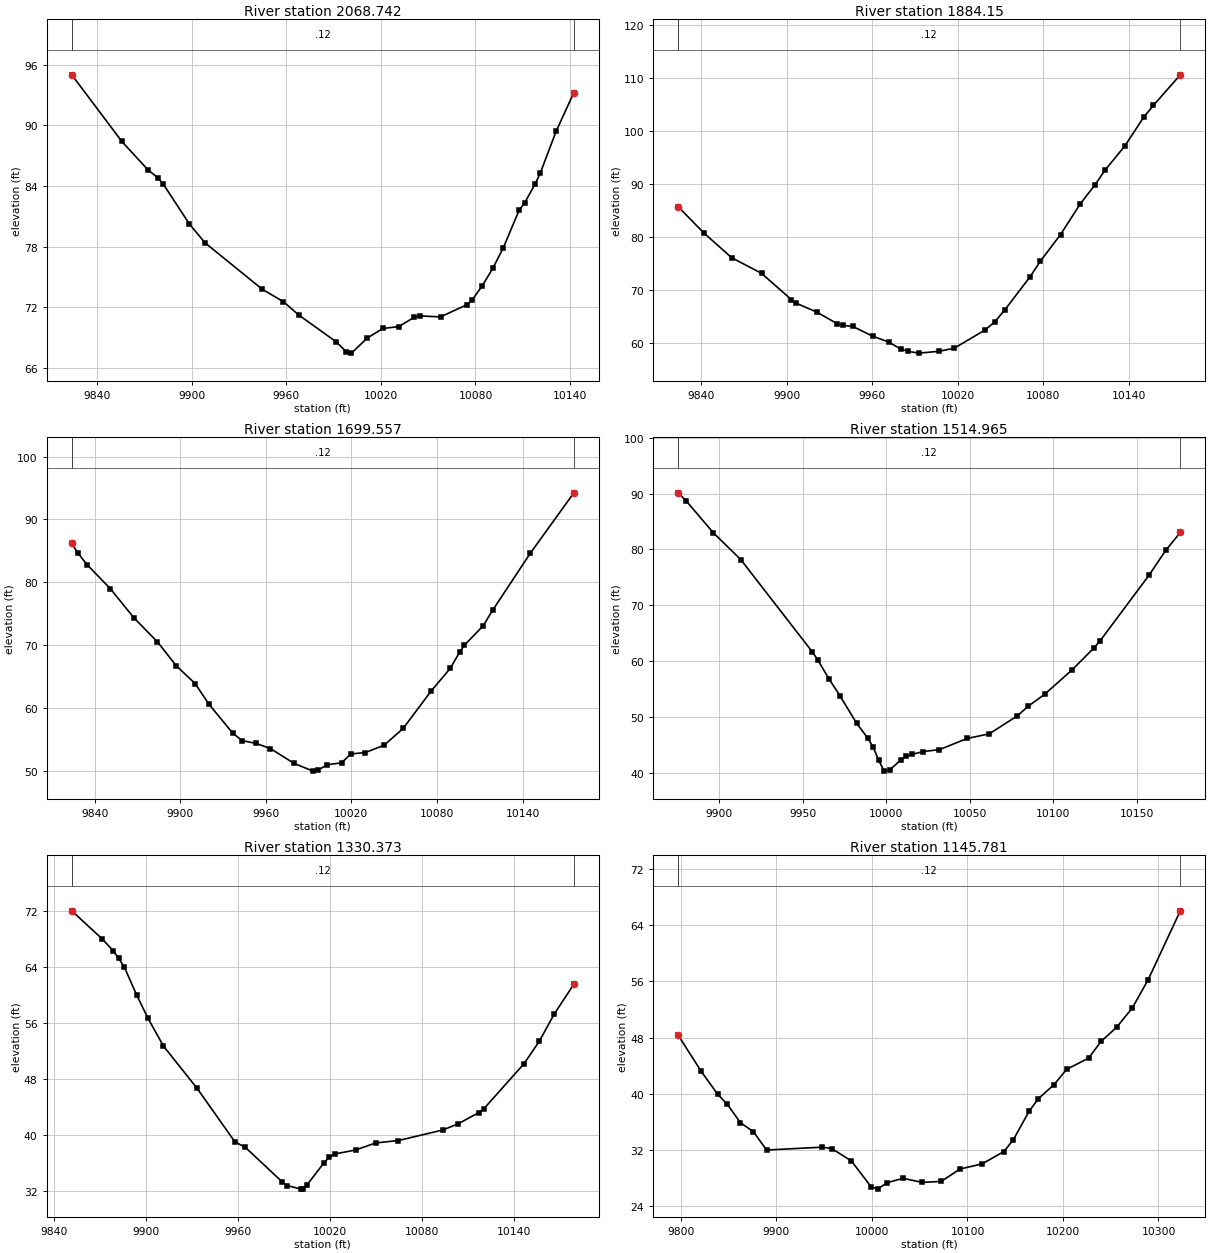
Type RM Length L Ch R = 1 ,2068.742,184.592100,184.592100,184.592100
XS GIS Cut Line= 6
  1252638.905412850532.5785694981252636.84653223850484.543666462
1252631.87673562850433.5463113281252619.89706472850358.841330591
1252604.87953551850262.4739379681252595.80742385850217.552983533
#Sta/Elev= 30
9824.02394.992739855.792  88.3999872.212 85.61539878.80484.775229882.10184.16823
9898.58380.243829908.47278.384269944.90373.772699958.19472.558879968.16271.21193
9991.42268.616189998.06767.6141910001.3867.4679110011.34 68.9569 10021.369.90576
10031.2770.0887310041.2371.0151610044.5571.1494710057.8371.0515710074.4472.25056
10077.7672.70429 10084.474.1560710091.0475.8700610097.6977.9081910107.7381.62059
10111.0882.3056810117.7784.1861710121.1285.2916210131.1689.4208910142.3693.23359
#Mann= 3 , 0 , 0
9824.023    0.12       09824.023    0.12       010142.36    0.12       0
#XS Ineff= 2 , 0
       0                10041.53       0
Bank Sta=9824.023,10142.36
Exp/Cntr=0.3,0.1

Type RM Length L Ch R = 1 , 1884.15,184.592100,184.592100,184.592100
XS GIS Cut Line= 6
1252841.37689537850435.0929001481252816.28803301850358.827880715
1252785.74384889850289.5101350831252741.88023745850181.657698777
1252728.49193285850139.3947825051252721.11897599850105.099408435
#Sta/Elev= 30
9824.02385.649539841.79380.755829861.50676.03016 9882.4173.090299903.354 68.1255
9906.91267.428629921.25365.758859935.59463.555859939.17963.28435 9946.35  63.076
9960.33461.227979971.44660.131089980.09758.791969985.33558.357669992.69958.03178
10006.7958.3777410017.4458.9531310038.7362.3418410045.83 63.909510052.9366.18728
10070.6772.4472410077.7775.3494610091.9780.3959610105.8786.21256 10116.289.79831
10123.0892.5250610136.8597.0479510150.37102.578810157.08104.774910175.95110.5463
#Mann= 3 , 0 , 0
9824.023    0.12       09824.023    0.12       010175.95    0.12       0
#XS Ineff= 2 , 0
       0                               0
Bank Sta=9824.023,10175.95
Exp/Cntr=0.3,0.1

Type RM Length L Ch R = 1 ,1699.557,184.592100,184.592100,184.592100
XS GIS Cut Line= 6
1252974.38340026850396.5990502471252963.01113941850276.077806247
1252954.78511844850222.7775011391252954.45632041850220.804713301
1252944.29666193850156.8023787561252933.90923479850047.122691969
#Sta/Elev= 30
9824.01286.210389828.05884.724769834.64982.819149851.12678.955289867.60374.32633
 9884.0870.503929897.26266.701689910.44363.87475 9920.3360.533069936.80755.98119
9943.39754.778869953.34454.329699963.30353.507259979.90251.14423 9993.1849.92141
  9996.550.0593110003.1450.9397110013.1151.2436810019.7552.6635410029.72 52.8769
10043.0154.04895 10056.356.7147610076.1462.7377910089.3366.2751410095.9268.88164
10099.2169.9808610112.3973.0565110118.9975.5237510145.3584.5878910175.9794.24218
#Mann= 3 , 0 , 0
9824.012    0.12       09824.012    0.12       010175.97    0.12       0
#XS Ineff= 2 , 0
       0                               0
Bank Sta=9824.012,10175.97
Exp/Cntr=0.3,0.1

Type RM Length L Ch R = 1 ,1514.965,184.592100,184.592100,184.592100
XS GIS Cut Line= 6
1253146.01874968850364.338138593 1253142.7250231850310.645604688
1253135.01296691850241.3490857941253134.11489269850231.382726688
1253121.48096424850147.8245028381253116.11973767850065.561020797
#Sta/Elev= 30
9875.48290.121349880.06688.738139896.50182.973829912.936 78.17039955.78161.65222
9959.08260.189239965.68456.847779972.28653.803739982.18948.930199988.79146.29486
9992.09344.664099995.39442.334229998.695 40.342510001.9840.5330610008.5942.31342
 10011.942.9623910015.2243.3234710021.8643.8277310031.8144.19009 10048.4 46.1834
10061.6747.0193910078.2750.19591 10084.951.9362810094.8454.1079210111.2858.47742
10124.4362.4244110127.7263.5531710157.3175.4127410167.1879.8118410175.9683.03159
#Mann= 3 , 0 , 0
9875.482    0.12       09875.482    0.12       010175.96    0.12       0
#XS Ineff= 2 , 0
       0                               0
Bank Sta=9875.482,10175.96
Exp/Cntr=0.3,0.1

Type RM Length L Ch R = 1 ,1330.373,184.592100,184.592100,184.592100
XS GIS Cut Line= 6
1253247.71714607850351.2335390891253288.62461973850266.919895785
1253303.85660596850215.2089340321253304.48906143850213.311567417
1253322.94173191850152.7441857161253333.65464607850038.733539088
#Sta/Elev= 30
9851.37971.989389871.06568.011749878.36566.309459882.01265.191449885.65863.96847
9893.613 60.01519901.129 56.64079911.18452.693979933.06446.681819957.75239.03711
9964.59338.245359988.53433.337719991.95432.79307   1000132.2861310002.24 32.2911
10004.5532.8234210015.96 36.064110019.3936.8534910022.8237.2968910036.5437.87286
10049.58 38.873710064.3239.2168210093.6540.7400210103.5341.6252910116.7143.18203
10120.0143.7178410146.3750.1913910156.26 53.367910166.1457.3078910178.8361.51179
#Mann= 3 , 0 , 0
9851.379    0.12       09851.379    0.12       010178.83    0.12       0
#XS Ineff= 2 , 0
       0                               0
Bank Sta=9851.379,10178.83
Exp/Cntr=0.3,0.1

Type RM Length L Ch R = 1 ,1145.781,190.963500,190.963500,190.963500
XS GIS Cut Line= 6
1253417.34815615850478.0844505731253473.68903098850284.268013296
1253474.26372669850282.3523607081253476.70174984 850273.87651997
1253489.20818135850196.5043887161253483.39422941849961.910622422
#Sta/Elev= 30
9797.161 48.32039821.29843.175279838.38139.942529848.63138.483139862.29835.87821
9875.96434.584659889.63131.989979947.71432.391219957.96432.188189978.46330.43052
9998.96326.77951 10005.826.4184310015.8727.3264510032.4927.9608910052.4327.38283
10072.3727.5092510092.2629.2865510115.2330.0069910138.2131.7770910148.0533.45197
10164.4637.4983710174.3139.3054210190.7241.3069210203.8443.4783710226.8245.07671
10239.9447.4561810256.3549.4961110272.7652.2519910289.1756.2406310322.8666.05178
#Mann= 3 , 0 , 0
9797.161    0.12       09797.161    0.12       010322.86    0.12       0
#XS Ineff= 2 , 0
       0                10092.29       0
Bank Sta=9797.161,10322.86
Exp/Cntr=0.3,0.1

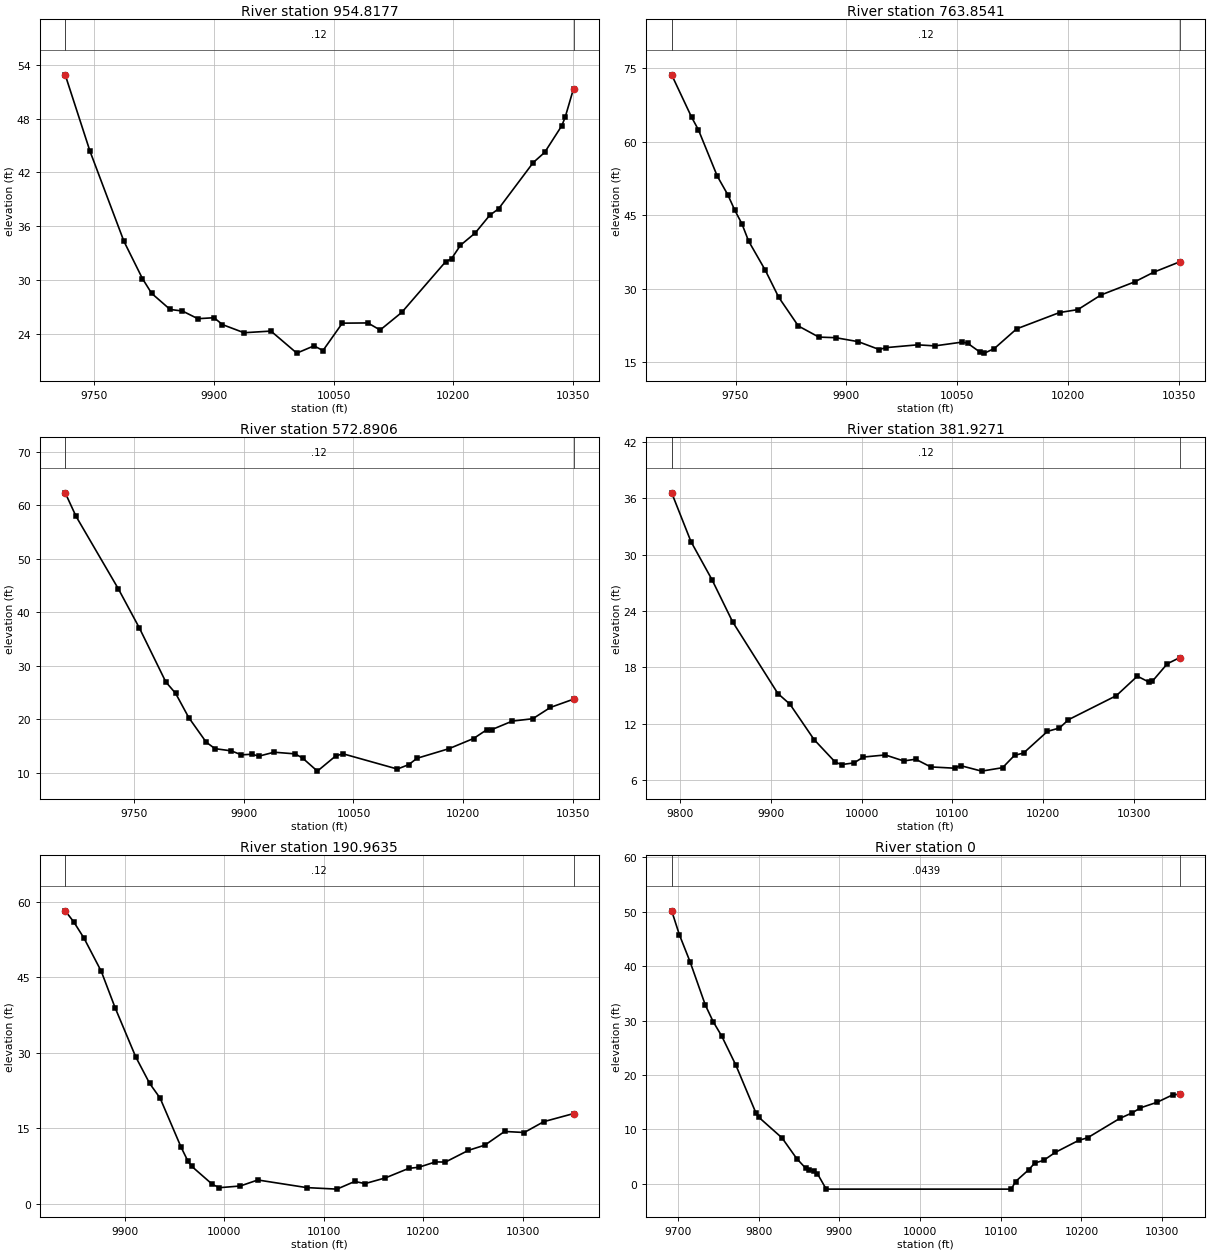
Type RM Length L Ch R = 1 ,954.8177,190.963600,190.963600,190.963600
XS GIS Cut Line= 6
1253492.50881274850569.9835390891253621.73550172850361.800021441
1253649.55569284850300.1035565121253740.47862218850135.780464122
1253771.61384884850072.5334233761253798.57539258850011.736822964
#Sta/Elev= 30
 9713.45 52.88219744.59544.33355 9787.11 34.29039810.27930.136879821.86428.48155
9845.03326.683649860.47926.511219879.78725.652449900.11725.762319910.67924.99416
9937.70924.085969971.50924.2707410003.8821.80914 10025.522.6219110036.7222.09541
10060.9825.1542410092.9625.1805410108.4224.3896610135.5226.3574210190.4532.00491
10197.9532.35508 10209.233.85702 10227.635.2193510245.8837.2033210256.8637.91599
10300.44 43.088610314.7944.2252210336.33 47.214610340.5848.1758510350.96 51.3358
#Mann= 3 , 0 , 0
 9713.45    0.12       0 9713.45    0.12       010350.96    0.12       0
#XS Ineff= 2 , 0
       09897.299        10082.11       0
Bank Sta=9713.45,10350.96
Exp/Cntr=0.3,0.1

Type RM Length L Ch R = 1 ,763.8541,190.963500,190.963500,190.963500
XS GIS Cut Line= 6
1253548.49839607850691.0772890891253837.03597243 850391.01762388
1253886.16079247850334.4761193091253939.78211692850257.394588924
1253965.22516262850211.9955368141253986.78208894850166.786172631
#Sta/Elev= 30
9663.67273.616669690.75264.924189699.80162.406329725.32652.945629739.61949.12905
9749.14745.948069758.62143.228649767.67139.697789790.29433.732529808.39228.22871
9834.90322.372989862.68820.099279885.31119.980229915.89519.17076 9944.2917.56468
9953.42417.951569996.18418.5235610019.47 18.306910056.6919.0842310063.8918.83702
10079.9417.1006510086.6116.8296510099.9517.7690410130.0721.78124 10188.125.11322
10212.8725.7094910244.12 28.698110289.4331.3557610315.5133.3480410350.9435.48332
#Mann= 3 , 0 , 0
9663.672    0.12       09663.672    0.12       010350.94    0.12       0
#XS Ineff= 2 , 0
       09878.062                       0
Bank Sta=9663.672,10350.94
Exp/Cntr=0.3,0.1

Type RM Length L Ch R = 1 ,572.8906,190.963500,190.963500,190.963500
XS GIS Cut Line= 6
1253689.12339607850827.7960390891253886.81761211850615.828115771
1253972.68176727850512.6046352671254012.53785331850449.219621497
1254035.27183215850403.6442972621254084.25584954850267.145377668
#Sta/Elev= 30
9655.81362.284199670.62157.894259728.34344.368839757.205 37.03219793.34926.94642
9806.80824.801359824.753 20.27449848.59915.680379860.64414.465689883.07514.05083
9896.70113.307329911.13213.422169920.75213.064279941.39713.802229970.21413.49098
9980.39812.7106410000.6610.2658810025.6913.10169 10035.713.50538   10110 10.6567
10125.4711.4706210136.8812.6651110180.6114.4616410214.2616.3643810232.0717.97831
 10239.218.02792 10267.319.6205610295.1920.05502 10319.322.1696510350.9523.71591
#Mann= 3 , 0 , 0
9655.813    0.12       09655.813    0.12       010350.95    0.12       0
#XS Ineff= 2 , 0
       0 9890.82                       0
Bank Sta=9655.813,10350.95
Exp/Cntr=0.3,0.1

Type RM Length L Ch R = 1 ,381.9271,190.963600,190.963600,190.963600
XS GIS Cut Line= 6
1254055.57567255850853.3357682551254068.77526621850740.652582884
 1254079.4313132850679.3687826481254097.70717925850622.061141636
1254103.80206712850593.952661481 1254138.0629074850299.899492766
#Sta/Elev= 30
9790.34336.589059811.62131.394719834.74427.351879857.55722.851939907.44515.22079
9920.76614.083669947.40610.312119970.8587.9010369977.7197.6537369991.4417.830644
10001.768.45474410025.988.67831910046.138.04145810059.488.222301   100767.404805
10102.42 7.2666710109.037.54132910132.156.95524410155.277.32082110168.488.638115
10178.398.87916510204.8111.1887410218.0311.5489910227.9412.4304910280.7814.99352
10303.9117.0660910317.1216.4165810320.4216.5211610336.9418.3867510350.9619.05434
#Mann= 3 , 0 , 0
9790.343    0.12       09790.343    0.12       010350.96    0.12       0
#XS Ineff= 2 , 0
       0                               0
Bank Sta=9790.343,10350.96
Exp/Cntr=0.3,0.1

Type RM Length L Ch R = 1 ,190.9635,190.963500,190.963500,190.963500
XS GIS Cut Line= 6
1254326.80467164850768.1261100781254302.73405822850696.957468795
1254241.56309296850535.4792832091254221.52155863850471.540050032
1254203.87625094850379.3246188831254197.11477396 850277.45258671
#Sta/Elev= 30
9840.04558.173419848.59855.986169858.98852.736829876.30546.161639890.15938.96934
9910.93929.191829924.91323.932619935.43421.012539956.47411.292629963.4888.469312
9966.9957.5166389988.0353.8878349995.049 3.2463410016.053.58397310033.624.774781
 10082.83.26102310113.152.95995810131.044.48445710141.364.05487510161.835.186846
10185.367.08013210195.457.29933410212.178.36010410222.138.32625510245.3710.66195
10261.8711.6910910281.64 14.4017 10301.414.19367 10321.116.3497510350.9417.94767
#Mann= 3 , 0 , 0
9840.045    0.12       09840.045    0.12       010350.94    0.12       0
#XS Ineff= 2 , 0
       0                               0
Bank Sta=9840.045,10350.94
Exp/Cntr=0.3,0.1

Type RM Length L Ch R = 1 ,       0,0.000000,0.000000,0.000000
XS GIS Cut Line= 6
1254566.80350685850795.1568431621254514.25669758850663.694990358
1254483.46888565850600.9712877991254409.80742477 850474.65210867
 1254383.6210299850425.0728135951254290.68589607850230.139789088
#Sta/Elev= 30
9692.29750.166579701.78145.797719715.20440.752019733.98832.845489743.79829.76567
9754.302 27.14079771.97321.741349796.94612.907179800.51412.175939829.0548.412146
 9847.214.6140989858.1742.8684849861.8292.4687029869.1382.3038319872.7931.858953
9883.757  -0.99910113.03  -0.99910118.340.39936710134.84 2.5920710142.113.801201
10153.014.27960710167.555.75615810196.637.97124610207.538.43615910247.5112.00632
10263.19 13.047810272.9613.9405410293.6814.9685710312.9416.3321610322.0616.46056
#Mann= 3 , 0 , 0
9692.297  0.0439       09692.297  0.0439       010322.06  0.0439       0
#XS Ineff= 2 , 0
       0                               0
Bank Sta=9692.297,10322.06
Exp/Cntr=0.3,0.1